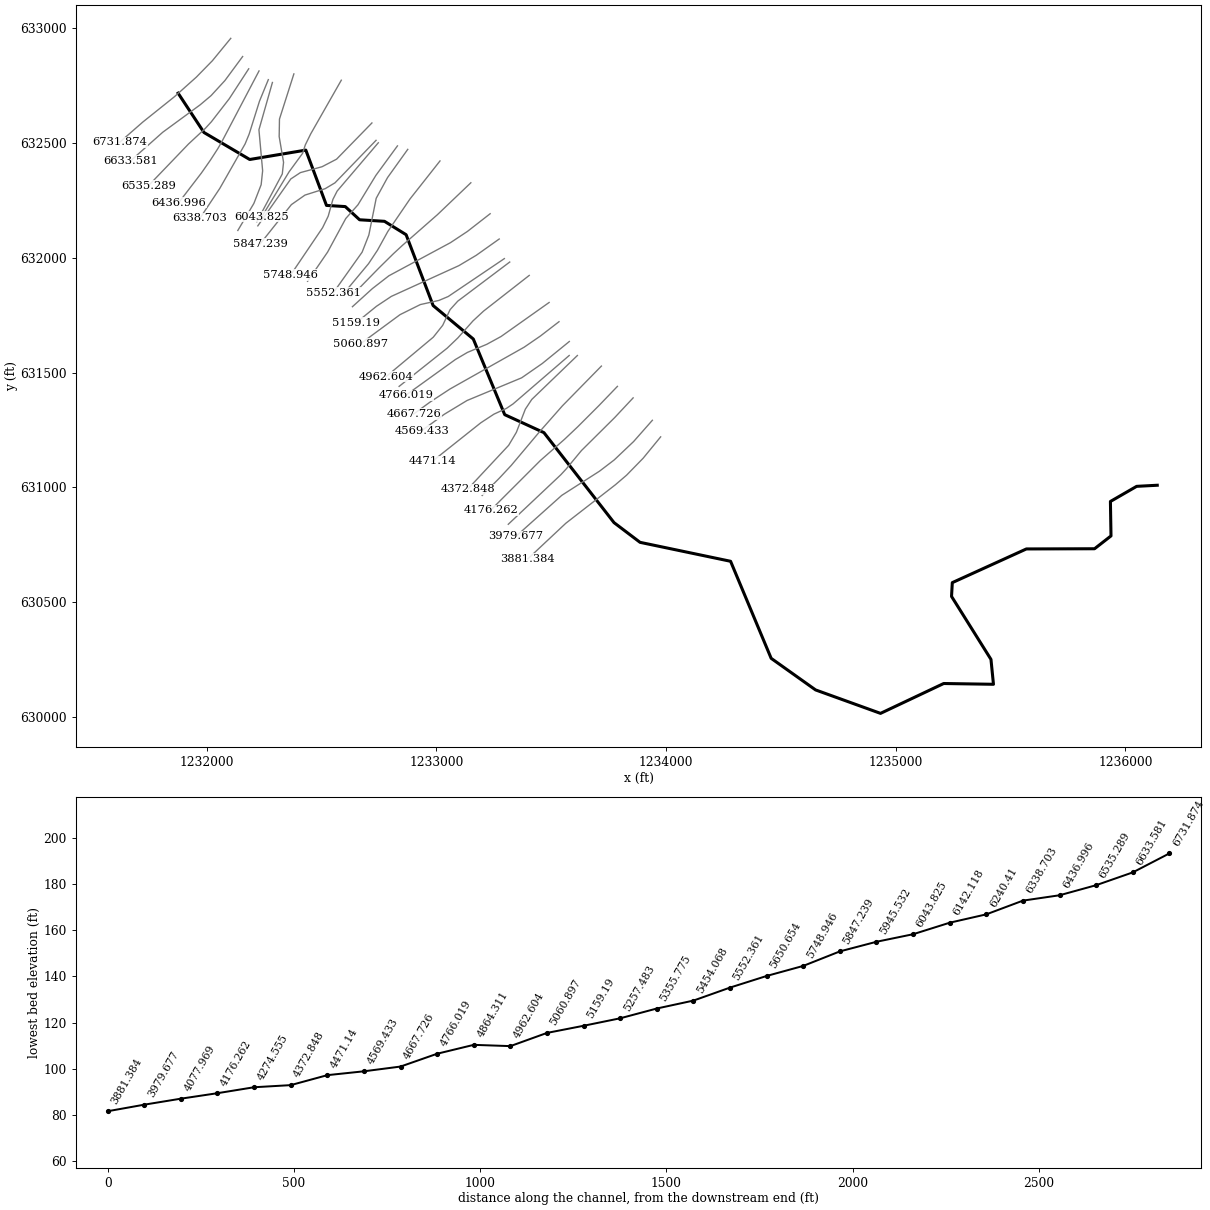
--- 689_ras.prj (project) ---

Proj Title=689
Current Plan=p01
Default Exp/Contr=0.3,0.1
English Units
Geom File=g01
Flow File=f01
Plan File=p01
Y Axis Title=Elevation
X Axis Title(PF)=Main Channel Distance
X Axis Title(XS)=Station
BEGIN DESCRIPTION:
RFD model 689 exported to HEC-RAS
END DESCRIPTION:

--- 689_ras.p01 (plan) ---

Plan Title=Plan 01
Program Version=4.10
Short Identifier=Plan 01
Geom File=g01
Flow File=f01
Subcritical Flow
Calc Critical at every XS
Secant Critical Depth

--- 689_ras.f01 (steady flow) ---

Flow Title=Flow 01
Program Version=5.01
Number of Profiles= 5
Profile Names=10yr,25yr,50yr,100yr,500yr
River Rch & RM=689,45,6731.874
  576.41   729.7  881.75  998.79 1265.12
River Rch & RM=689,45,6633.581
  582.53  738.58  892.79 1012.88 1285.53
River Rch & RM=689,45,6535.289
  584.39  741.29  896.15 1017.18 1291.77
River Rch & RM=689,45,6338.703
  587.62  745.99  902.01 1024.66 1302.64
River Rch & RM=689,45, 6240.41
  589.92  749.33  906.16 1029.97 1310.36
River Rch & RM=689,45,6142.118
  593.11  753.98  911.95 1037.37 1321.12
River Rch & RM=689,45,6043.825
  596.27  758.59  917.68 1044.72 1331.83
River Rch & RM=689,45,5945.532
  597.62  760.56  920.13 1047.86  1336.4
River Rch & RM=689,45,5748.946
  602.96  768.36  929.85 1060.31 1354.58
River Rch & RM=689,45,5650.654
  612.15  781.79  946.57  1081.8    1386
River Rch & RM=689,45,5552.361
  616.45  788.09  954.42  1091.9 1400.79
River Rch & RM=689,45,5454.068
  618.58  791.21  958.32 1096.92 1408.15
River Rch & RM=689,45,5355.775
  621.55  795.56  963.74 1103.91 1418.41
River Rch & RM=689,45,5257.483
  625.75  801.73  971.43 1113.82 1432.98
River Rch & RM=689,45,5060.897
  632.39  811.48  983.58 1129.53 1456.09
River Rch & RM=689,45,4962.604
   637.7   819.3  993.34 1142.14 1474.69
River Rch & RM=689,45,4864.311
  640.53  823.47  998.54 1148.88 1484.64
River Rch & RM=689,45,4667.726
  643.74  828.21 1004.46 1156.53 1495.96
River Rch & RM=689,45,4569.433
  647.73  834.09 1011.79 1166.04 1510.02
River Rch & RM=689,45,4372.848
  653.24  842.23 1021.96 1179.24 1529.57
River Rch & RM=689,45,4274.555
  655.97  846.27    1027 1185.78 1539.28
River Rch & RM=689,45,4176.262
  660.23  852.56 1034.86 1196.01 1554.45
River Rch & RM=689,45,4077.969
  662.15  855.41 1038.41 1200.63 1561.32
River Rch & RM=689,45,3979.677
  669.37  866.11 1051.78 1218.04 1587.22
River Rch & RM=689,45,3881.384
  672.75  871.12 1058.05 1226.21  1599.4
River Rch & RM=689,45,3684.798
  673.87  872.79 1060.13 1228.92 1603.44
River Rch & RM=689,45,3487.075
  678.33   879.4  1068.4 1239.72 1619.55
River Rch & RM=689,45,3241.749
  686.02  890.84  1082.7  1258.4 1647.48
River Rch & RM=689,45,3054.013
  687.83  893.54 1086.07 1262.82 1654.09
River Rch & RM=689,45,2866.277
  693.58   902.1 1096.78 1276.84  1675.1
River Rch & RM=689,45,2678.541
   698.9  910.04 1106.72 1289.87 1694.65
River Rch & RM=689,45,2490.806
  702.07  914.77 1112.63 1297.63  1706.3
River Rch & RM=689,45, 2303.07
  704.17   917.9 1116.55 1302.77 1714.04
River Rch & RM=689,45,1969.288
  707.64  923.09 1123.05 1311.31 1726.89
Boundary for River Rch & Prof#=689,45,1
Up Type= 0
Dn Type= 2
Boundary for River Rch & Prof#=689,45,2
Up Type= 0
Dn Type= 2
Boundary for River Rch & Prof#=689,45,2
Up Type= 0
Dn Type= 2
Boundary for River Rch & Prof#=689,45,2
Up Type= 0
Dn Type= 2
Boundary for River Rch & Prof#=689,45,2
Up Type= 0
Dn Type= 2

--- 689_ras.g01 (geometry) ---

Geom Title=689
Program Version=4.10

River Reach=689,45
Reach XY= 30
1231876.04224982632716.479505007 1231988.6575732632545.351714988
 1232187.8241777632427.8517440741232431.99077351632468.685058185
1232521.99073995632227.8517937311232603.65738238632222.851792816
1232666.15736228632165.3518080971232774.49066346632158.685140246
1232868.65730063632100.3518214911232986.15725706 631792.01857626
 1233161.1572012631646.1852811471233297.82381795631317.018708205
1233468.65709863631238.6853931541233773.65699724630847.018833872
1233886.99029464 630761.18552276 1234281.1568426630678.685535766
1234457.82344485630256.1856560421234651.15671715630118.685691248
1234933.86532568 630016.579731371235208.86524833630146.579684845
1235425.53185099630143.2463461661235414.69852398630251.579647679
1235243.03191595630525.7462379341235246.36525004630585.746220039
1235568.86515918630732.4128337981235865.53173833630733.246158253
1235937.19838547630789.0794729311235934.69839058630939.079428445
1236048.86502548631004.9127389481236138.63204435631009.699240715

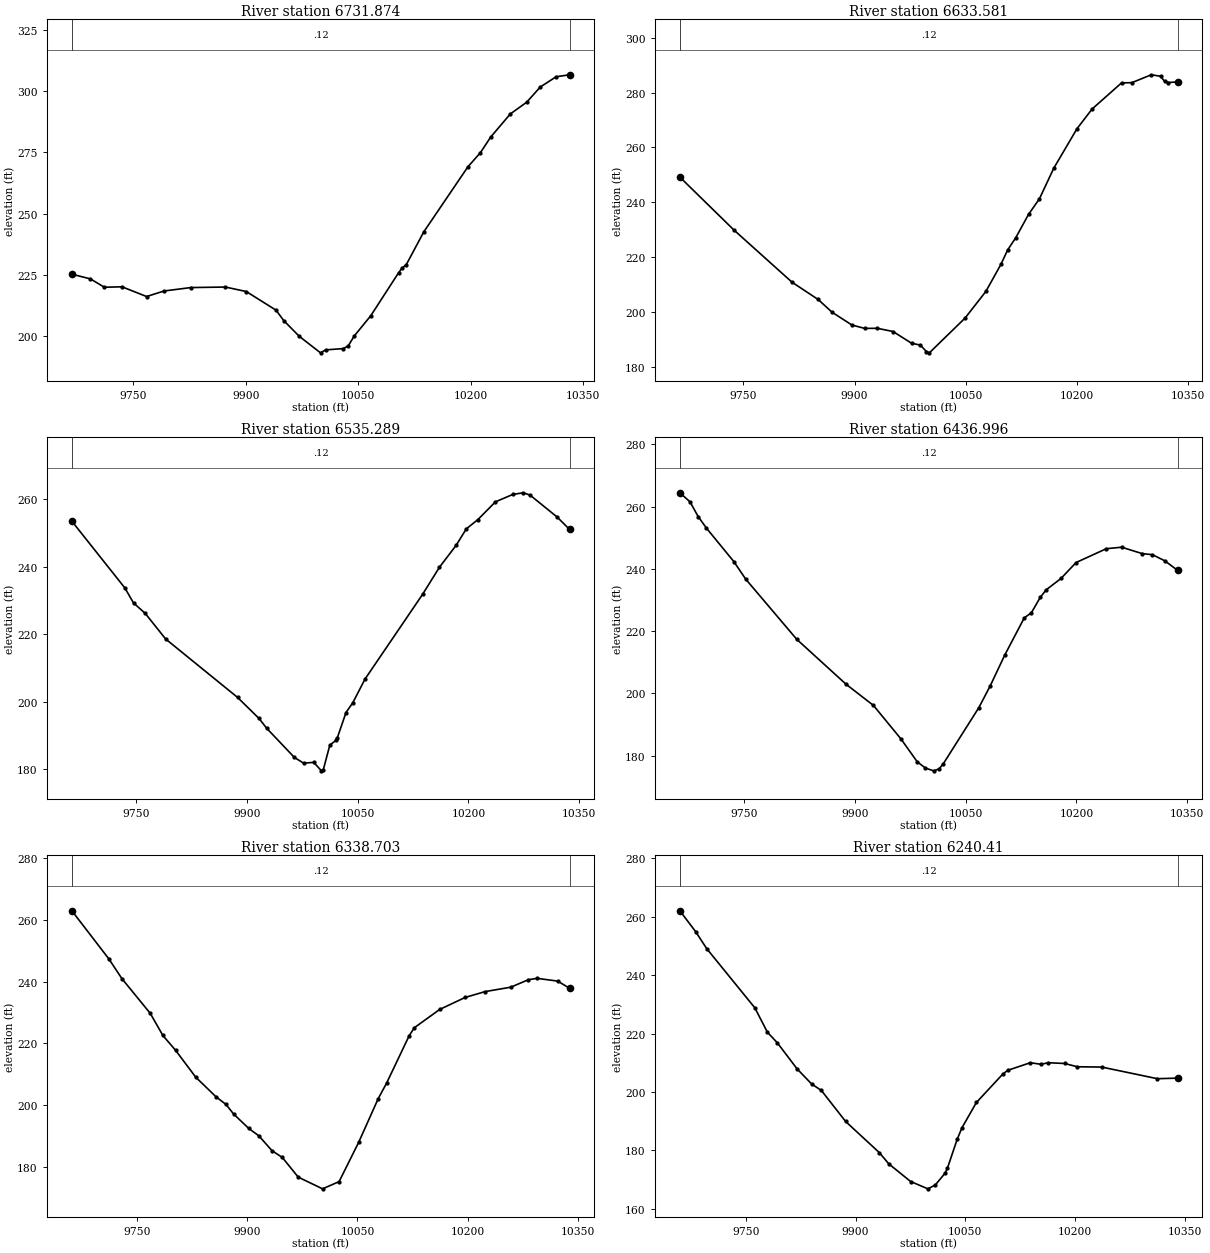
Type RM Length L Ch R = 1 ,6731.874,98.292800,98.292800,98.292800
XS GIS Cut Line= 6
1232105.25250728632955.2518070891232025.37233635632857.907217338
1231955.67539517 632786.626700161231860.36655594632701.325164206
1231722.58043064632590.9931699421231622.09792102632503.158246651
#Sta/Elev= 30
9668.223225.33599693.069 223.4089711.502220.01489735.073220.18989767.874216.2218
9791.082218.47849826.843 219.8789873.028220.09179900.771218.25569940.449210.6463
9950.648206.43639971.311200.01219999.757193.243110006.54194.455210029.97194.9699
10036.55196.047210044.96200.213910066.71208.3705 10103.8225.9096 10108.7227.9066
10113.95229.150910137.43242.612210196.27269.163510212.91274.9182 10226.7281.3237
10252.79 290.72810274.63295.513410292.67301.703310313.85305.896810331.77306.7094
#Mann= 3 , 0 , 0
9668.223    0.12       09668.223    0.12       010331.77    0.12       0
#XS Ineff= 2 , 0
       0                               0
Bank Sta=9668.223,10331.77
Exp/Cntr=0.3,0.1

Type RM Length L Ch R = 1 ,6633.581,98.292700,98.292700,98.292700
XS GIS Cut Line= 6
1232156.99005591632876.0252166351232079.85365903632771.515416861
1232019.55416238632705.8811642531231972.46152501632666.118208396
1231809.07026745632546.3708071831231668.58488814632421.519989973
#Sta/Elev= 30
9664.348249.14439737.318229.83949815.794210.76569850.904204.49389869.586199.8683
9896.459195.17669913.635193.9533 9930.81193.9824 9951.95192.81119976.986188.5117
9988.824187.86919997.018185.4585 10000.9185.032510049.08197.713210077.19207.4607
 10097.4217.296110106.58222.5978 10117.3 226.95610134.75235.565210149.36241.2209
10168.72252.388310199.95266.757410220.44273.989310260.14283.514810274.02283.5905
10300.27286.475110312.78285.9413 10318.1284.101410322.56283.654710335.69283.8547
#Mann= 3 , 0 , 0
9664.348    0.12       09664.348    0.12       010335.69    0.12       0
#XS Ineff= 2 , 0
       0                               0
Bank Sta=9664.348,10335.69
Exp/Cntr=0.3,0.1

Type RM Length L Ch R = 1 ,6535.289,98.292800,98.292800,98.292800
XS GIS Cut Line= 6
1232183.38332687632822.6030293791232099.09180261632692.907932068
1232021.15358715632592.3620701721231994.33369813632563.058946763
1231921.31497309632495.260898807 1231746.5309672632313.227917437
#Sta/Elev= 30
9663.139253.41469734.853233.65679746.601229.21189762.424226.12719790.091218.5382
9887.423201.24739916.518195.00519926.941 192.0919964.406183.45919976.761181.7843
9990.603182.0001   10001179.499710003.43179.759810012.37187.120110020.63188.5189
10022.52189.291410034.25196.766210043.46199.663810059.98206.671910137.96231.7675
10160.73239.774910183.44246.300710197.09251.143310212.84253.905110236.52259.1442
10260.21261.356310274.42261.8307 10283.5261.124610319.89254.677610336.88250.9939
#Mann= 3 , 0 , 0
9663.139    0.12       09663.139    0.12       010336.88    0.12       0
#XS Ineff= 2 , 0
       0                               0
Bank Sta=9663.139,10336.88
Exp/Cntr=0.3,0.1

Type RM Length L Ch R = 1 ,6436.996,98.292800,98.292800,98.292800
XS GIS Cut Line= 6
1232228.31209085632813.3510978911232066.16624918632504.798702967
1232049.34316044632475.6804707511232016.39350658632424.618653384
1231977.55535805632369.079502019 1231878.3927187632239.676845509
#Sta/Elev= 30
9663.108 264.4589676.833 261.5579687.954256.80939699.076253.11259736.147242.3678
 9752.33236.6998 9821.41 217.3769888.137202.95329925.208196.14619962.279185.4378
9984.522178.03149995.643176.018810006.71175.138310014.15175.7742 10019.8177.4268
10067.87195.436610083.49202.535510103.01212.354810129.36224.273810138.96225.8902
10150.97230.834310158.98233.269110179.11236.941810199.54242.055810240.41246.4895
 10261.2246.976410289.06244.916410302.89244.568410319.57242.615910336.88239.5575
#Mann= 3 , 0 , 0
9663.108    0.12       09663.108    0.12       010336.88    0.12       0
#XS Ineff= 2 , 0
       0                               0
Bank Sta=9663.108,10336.88
Exp/Cntr=0.3,0.1

Type RM Length L Ch R = 1 ,6338.703,98.292700,98.292700,98.292700
XS GIS Cut Line= 6
1232268.76360159632775.4462946251232230.26011642632681.532334332
1232185.24081348632538.1897837161232167.74917589632495.709238285
1232057.61999719632302.1603512621231970.49583832632171.154065659
#Sta/Elev= 30
  9661.1263.02729711.653247.36349729.343240.98469767.864229.75539785.058222.5682
9802.252217.79949829.763209.05689857.273 202.7149871.029200.19019881.345197.1091
9901.978192.42329915.825190.00959933.565185.22769947.757182.98789969.445 176.615
10002.53172.819110025.07175.158210051.72187.905410078.37202.092310089.79207.1283
10120.25222.369410127.49225.074610162.13231.025610196.71234.907610223.91236.8075
10258.89238.234910282.86 240.66810294.84241.103710322.81240.213510338.95237.8892
#Mann= 3 , 0 , 0
  9661.1    0.12       0  9661.1    0.12       010338.95    0.12       0
#XS Ineff= 2 , 0
       0                               0
Bank Sta=9661.1,10338.95
Exp/Cntr=0.3,0.1

Type RM Length L Ch R = 1 , 6240.41,98.292800,98.292800,98.292800
XS GIS Cut Line= 6
1232286.59801796632763.0622377111232227.91851327632557.175368022
1232244.02222077632378.7547472011232237.54144211 632317.98076528
1232205.99324146632236.7931561111232136.01810318632118.837990207
#Sta/Elev= 30
9659.642261.97639681.186254.8642 9696.27249.0691 9762.23228.77169779.395220.4371
9792.904216.84379819.921207.9251 9839.93202.72979853.224200.52279886.336189.9305
9932.348179.29659945.477 175.4119975.335169.38399998.881166.884910008.94168.1829
10022.35172.232410025.67173.995210038.88183.793910045.48187.774710065.23196.4187
10101.57206.202510108.24207.431210138.98210.013910153.54209.478310163.47210.0096
10185.86209.755210203.11208.633110236.69208.525710312.78  204.5510340.32204.7446
#Mann= 3 , 0 , 0
9659.642    0.12       09659.642    0.12       010340.32    0.12       0
#XS Ineff= 2 , 0
       0                               0
Bank Sta=9659.642,10340.32
Exp/Cntr=0.3,0.1

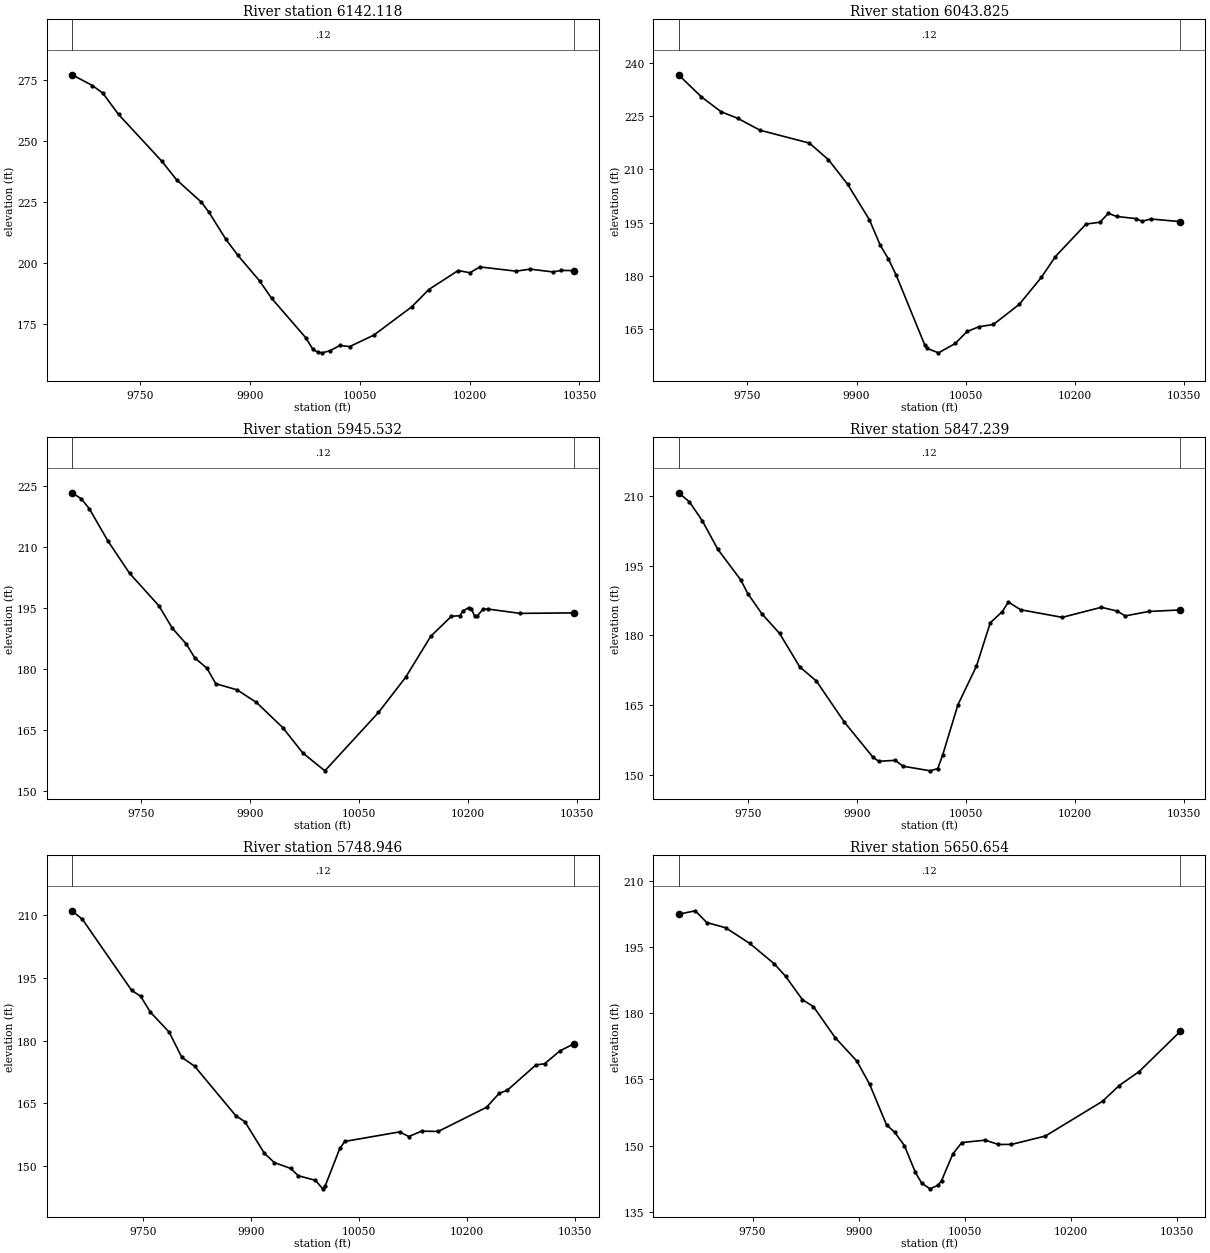
Type RM Length L Ch R = 1 ,6142.118,98.292800,98.292800,98.292800
XS GIS Cut Line= 6
1232380.03460277632800.4428486311232317.31750784632603.834543247
1232316.01317231632527.5409249691232335.12253885 632415.43939717
1232329.55587951632364.8111561151232218.64034798  632156.8632543
#Sta/Elev= 30
9657.603277.19489685.344272.79869699.628269.65139720.968260.96129779.945241.8269
9800.393234.11269834.181 224.9699844.179220.96529867.472209.80179883.914203.2053
9913.503192.73859929.924185.61169976.248169.54719986.303164.68819993.006163.4847
    9999 163.26810009.77164.162510023.15166.280610036.48165.831510069.42170.5302
10121.08182.113910144.44189.201910184.52196.999710200.32  196.0810214.35198.4646
 10263.5196.733510282.84 197.56510313.78196.411910325.38 197.04810342.38196.9601
#Mann= 3 , 0 , 0
9657.603    0.12       09657.603    0.12       010342.38    0.12       0
#XS Ineff= 2 , 0
       0                               0
Bank Sta=9657.603,10342.38
Exp/Cntr=0.3,0.1

Type RM Length L Ch R = 1 ,6043.825,98.292800,98.292800,98.292800
XS GIS Cut Line= 6
1232586.44843668 632772.981203511232453.30567935632539.240317836
1232429.81623823632491.3974272821232417.98276867632454.613359872
1232359.29441594632374.3003574871232240.65945274632179.195065523
#Sta/Elev= 30
9655.543236.66429686.835230.4571 9714.09226.22019736.905 224.3869767.324 221.041
 9835.11217.41529861.368212.72679887.627205.81679917.636195.78589932.433188.6315
9943.398184.86019954.363180.19149993.561160.51289996.996159.517610012.42158.2851
10035.43160.9277 10051.7164.303310067.97165.638110087.83166.283110123.29171.9349
10153.86179.622110172.98185.431110215.02194.580110234.13195.1073 10245.6197.6078
10257.06196.722610284.11196.111110291.85195.353810303.82 196.01110344.46195.2745
#Mann= 3 , 0 , 0
9655.543    0.12       09655.543    0.12       010344.46    0.12       0
#XS Ineff= 2 , 0
       0                               0
Bank Sta=9655.543,10344.46
Exp/Cntr=0.3,0.1

Type RM Length L Ch R = 1 ,5945.532,98.292700,98.292700,98.292700
XS GIS Cut Line= 6
1232719.75733889632586.8530136541232566.03746612632429.305039306
1232502.68719295632396.281678283 1232408.3651889632370.720620404
 1232366.5673409632343.0196145561232223.04429608632138.942064701
#Sta/Elev= 30
9654.731223.32219667.497221.84169678.681219.34779704.045211.48669733.908203.5331
9774.122195.58719792.871190.01499811.747186.21449823.676182.76569840.535180.1766
9852.481176.42219881.722174.91739908.525171.81159944.625165.64839972.239159.4214
10002.58155.020110076.41169.358810113.83178.018210148.52188.114210176.75192.9783
10188.55 193.13810192.48194.303510200.34195.051810204.27194.869410208.67 192.986
10212.14193.0346   10220194.674610226.53194.773510271.12193.700710345.26193.8199
#Mann= 3 , 0 , 0
9654.731    0.12       09654.731    0.12       010345.26    0.12       0
#XS Ineff= 2 , 0
       0                               0
Bank Sta=9654.731,10345.26
Exp/Cntr=0.3,0.1

Type RM Length L Ch R = 1 ,5847.239,98.292800,98.292800,98.292800
XS GIS Cut Line= 6
1232737.71673095632511.2343800581232559.17167214632326.352479025
1232516.33090182632300.8173063051232428.46912462632272.962333265
1232369.09429575632231.3337305531232233.55808726632060.959088028
#Sta/Elev= 30
9654.693210.68959669.631208.74939687.324204.69159708.743198.53589740.375191.9157
9750.092188.97429769.525184.62859793.817180.41119821.513173.22749844.411170.1786
9883.055 161.317 9922.14153.81199930.079152.91299952.817153.12339963.728151.8541
10001.25150.859910011.42 151.35310018.21154.2649 10039.2165.0821 10064.7173.3926
10083.74182.7269 10100.2185.106910108.61187.173910125.43185.525210182.65183.8862
10236.63186.049610258.38  185.2310269.42 184.19510301.91185.151210345.26185.4769
#Mann= 3 , 0 , 0
9654.693    0.12       09654.693    0.12       010345.26    0.12       0
#XS Ineff= 2 , 0
       0                               0
Bank Sta=9654.693,10345.26
Exp/Cntr=0.3,0.1

Type RM Length L Ch R = 1 ,5748.946,98.292800,98.292800,98.292800
XS GIS Cut Line= 6
1232747.57043688632500.5920059511232568.58097136632290.618331023
1232549.83579111 632253.887247731232529.54334922632181.162083117
1232504.96484745632130.8151542831232365.78850246631924.996170647
#Sta/Elev= 30
9651.253211.06669665.653209.01869733.957192.05829746.764190.59489759.852186.8775
9786.246182.04799803.841 176.0099821.437173.93739878.623162.11229891.702160.5831
9918.534153.08449932.473150.86259954.951149.47129965.643147.72089989.527146.6185
9999.695144.582810003.06 145.26510023.41154.244210030.33155.916310106.48158.1984
10119.32157.091410137.04158.370810160.32158.311810227.37  164.0810244.93167.4197
 10256.2168.1426   10296174.211710308.11174.4863 10329.4177.573210348.75179.2465
#Mann= 3 , 0 , 0
9651.253    0.12       09651.253    0.12       010348.75    0.12       0
#XS Ineff= 2 , 0
       0                               0
Bank Sta=9651.253,10348.75
Exp/Cntr=0.3,0.1

Type RM Length L Ch R = 1 ,5650.654,98.292700,98.292700,98.292700
XS GIS Cut Line= 6
1232830.87854576632486.9984709611232736.92046563632358.472194983
1232658.92313836632230.4837381041232605.86008492632170.795833776
1232526.68381432632024.4919762911232439.79084321631897.650603223
#Sta/Elev= 30
9645.317202.43229668.888203.22059685.243200.55919711.989199.36989745.974195.8288
9780.645191.20869796.724188.36459820.363 183.0929835.969181.52359866.799174.4726
9897.342169.19329915.387163.9484 9939.34154.71769950.794153.06849964.588150.0387
9980.082143.97669989.186141.4881   10001140.230710012.17141.049910017.12142.0842
10033.08148.126410045.72150.713210078.95  151.2610097.39150.284810116.01150.2954
10164.02152.199710244.68160.067510268.25163.633710296.51166.803210354.68175.9166
#Mann= 3 , 0 , 0
9645.317    0.12       09645.317    0.12       010354.68    0.12       0
#XS Ineff= 2 , 0
       0                               0
Bank Sta=9645.317,10354.68
Exp/Cntr=0.3,0.1

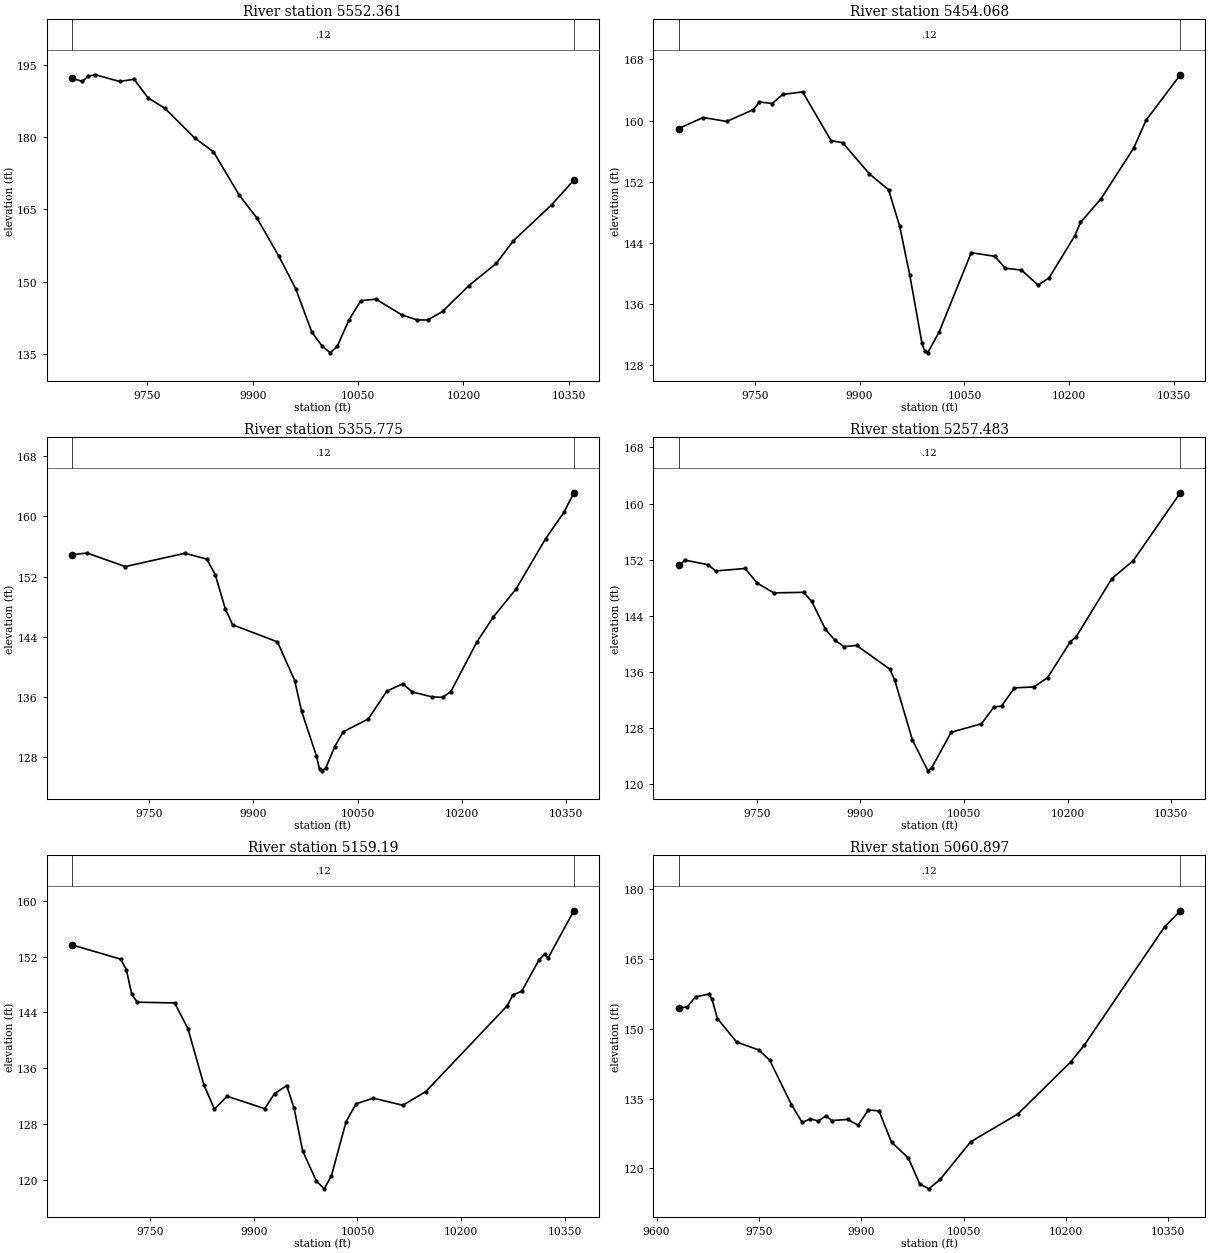
Type RM Length L Ch R = 1 ,5552.361,98.292800,98.292800,98.292800
XS GIS Cut Line= 6
1232875.75511531632471.9092381341232787.68164671632348.872245139
1232738.38510651632258.9224479641232706.47386983632099.215008731
1232677.09807552632024.3668621831232551.98557794631848.084505307
#Sta/Elev= 30
9642.583192.14479657.408191.54549665.574192.6173 9675.66192.9034 9710.49191.5092
9730.906191.98159750.835  188.119774.618185.97519817.299179.78179843.995 176.937
9880.919167.8858 9906.12163.13879937.428155.1959 9961.12148.52499984.226139.4805
    9999136.588210010.61 135.20510020.49136.602610037.03142.019410053.74146.0193
10075.34146.353610112.59143.059910134.43142.023410149.23142.0235 10170.3143.7842
10207.71149.136210246.81 153.75810271.37158.480110325.58165.898910357.42171.0446
#Mann= 3 , 0 , 0
9642.583    0.12       09642.583    0.12       010357.42    0.12       0
#XS Ineff= 2 , 0
       0                               0
Bank Sta=9642.583,10357.42
Exp/Cntr=0.3,0.1

Type RM Length L Ch R = 1 ,5454.068,98.292800,98.292800,98.292800
XS GIS Cut Line= 6
1233016.14021294 632421.546157391232885.34195287632255.699300959
1232788.82707002632114.104750526 1232744.0339277632032.916142785
1232705.17398796631974.3725627451232595.24788779631842.214733278
#Sta/Elev= 30
9641.155158.95339676.342 160.3969710.166159.88279748.317161.43749756.795162.4322
9775.129162.2308 9789.95163.41169818.589 163.7569859.206157.3784 9875.95157.0872
9914.085153.01869941.525150.94099957.205146.23829971.835139.77549989.333130.8283
9993.429129.78029997.525129.576910013.95132.325510059.73  142.6910093.45 142.219
10108.44140.662310131.65140.418210155.28138.449710171.03139.387410207.67144.8783
10216.03146.650610245.14149.728810292.24156.417410309.64160.0256 10358.8165.9935
#Mann= 3 , 0 , 0
9641.155    0.12       09641.155    0.12       0 10358.8    0.12       0
#XS Ineff= 2 , 0
       0                               0
Bank Sta=9641.155,10358.8
Exp/Cntr=0.3,0.1

Type RM Length L Ch R = 1 ,5355.775,98.292800,98.292800,98.292800
XS GIS Cut Line= 6
1233150.44115749  632326.48532851233004.65134825632187.334939466
1232853.72813595632054.9456808791232813.29082013632017.621019403
1232749.71320717 631954.908951621232627.50587292631829.736148564
#Sta/Elev= 30
9639.214154.92799660.857155.12979715.807153.33359801.659155.10859833.084154.3211
9845.192152.21719859.515147.73339870.014145.58839934.551143.31479959.373138.1574
9969.301134.07389990.661128.11849995.032126.38219999.086 126.14910004.06126.5388
10016.77129.337410029.17131.344710065.14133.048310091.92136.778110114.82 137.722
10128.64136.639410156.29136.003710172.07135.921410183.94136.705910221.48143.3207
10244.96146.618810277.78 150.366 10320.1157.033910346.56 160.56710360.79 163.154
#Mann= 3 , 0 , 0
9639.214    0.12       09639.214    0.12       010360.79    0.12       0
#XS Ineff= 2 , 0
       0                               0
Bank Sta=9639.214,10360.79
Exp/Cntr=0.3,0.1

Type RM Length L Ch R = 1 ,5257.483,98.292700,98.292700,98.292700
XS GIS Cut Line= 6
1233234.47957942632191.6960675581233135.45911786632114.590110585
1233061.64537414632065.686815794  1232793.890868631921.739265502
1232721.66617076631865.6816414211232634.92469742631786.961097555
#Sta/Elev= 30
9636.535151.17859646.386151.92839679.624151.28229690.106150.39699732.995150.7472
9750.451148.65739774.493147.27029817.784147.3534 9829.59146.04799849.268142.1025
9862.718 140.5639876.079139.61419894.521139.78639942.421136.41839949.741134.8415
9975.363126.30979997.828121.925510003.17122.341510031.51127.4156 10075.3128.6316
10093.54131.026810104.45131.149210123.21133.745310151.19133.872910171.04135.1885
10204.05140.297710212.49141.012910264.18149.3029 10295.2151.858610363.44161.5303
#Mann= 3 , 0 , 0
9636.535    0.12       09636.535    0.12       010363.44    0.12       0
#XS Ineff= 2 , 0
       0                               0
Bank Sta=9636.535,10363.44
Exp/Cntr=0.3,0.1

Type RM Length L Ch R = 1 , 5159.19,98.292800,98.292800,98.292800
XS GIS Cut Line= 6
1233273.90055555632081.6793341771233173.89313597632010.688845329
1233098.25386833 631965.669804331232804.43958496631831.948934342
1232739.57653361631788.8051459181232650.09715794631716.152550903
#Sta/Elev= 30
9636.538153.69999707.132151.64719715.168150.13169723.084146.5927    9731145.4771
9785.185145.36619804.429141.66739827.447133.62099842.719130.1374 9861.17131.9739
9915.593130.19559929.792132.35259947.542133.51219958.191130.25629970.527124.1457
9990.443119.801710001.81 118.68510012.21120.536110033.52128.339910047.98130.8937
10072.81131.697910115.78130.679710149.05132.655810266.82144.955810275.11146.5129
10287.97147.050110312.93151.542510321.51152.4051 10325.8151.764810363.46158.5985
#Mann= 3 , 0 , 0
9636.538    0.12       09636.538    0.12       010363.46    0.12       0
#XS Ineff= 2 , 0
       0                               0
Bank Sta=9636.538,10363.46
Exp/Cntr=0.3,0.1

Type RM Length L Ch R = 1 ,5060.897,98.292800,98.292800,98.292800
XS GIS Cut Line= 6
 1233296.3129949631996.325286156 1233051.9492409631831.327932069
1233011.37039201631814.2445569351232930.53948745631796.242105781
1232842.16322955 631752.335629171232669.50667597631625.158220586
#Sta/Elev= 30
9632.279154.46339645.106154.74929657.175156.88639677.291157.48059681.314 156.367
 9689.36   152.29717.522147.14959749.708145.4736  9765.8143.28179797.824133.6833
9813.557  129.869825.356130.65019837.156130.17559848.544131.30949856.822130.2799
9880.254130.51689895.547129.27539910.522132.58139926.133132.32289944.414125.6233
9969.043122.24189985.818116.6479 9999.16115.5942 10015.8117.627510060.37125.7077
10129.77131.706210206.81142.842110226.89146.472610344.55171.919210367.73175.3881
#Mann= 3 , 0 , 0
9632.279    0.12       09632.279    0.12       010367.73    0.12       0
#XS Ineff= 2 , 0
       0                               0
Bank Sta=9632.279,10367.73
Exp/Cntr=0.3,0.1

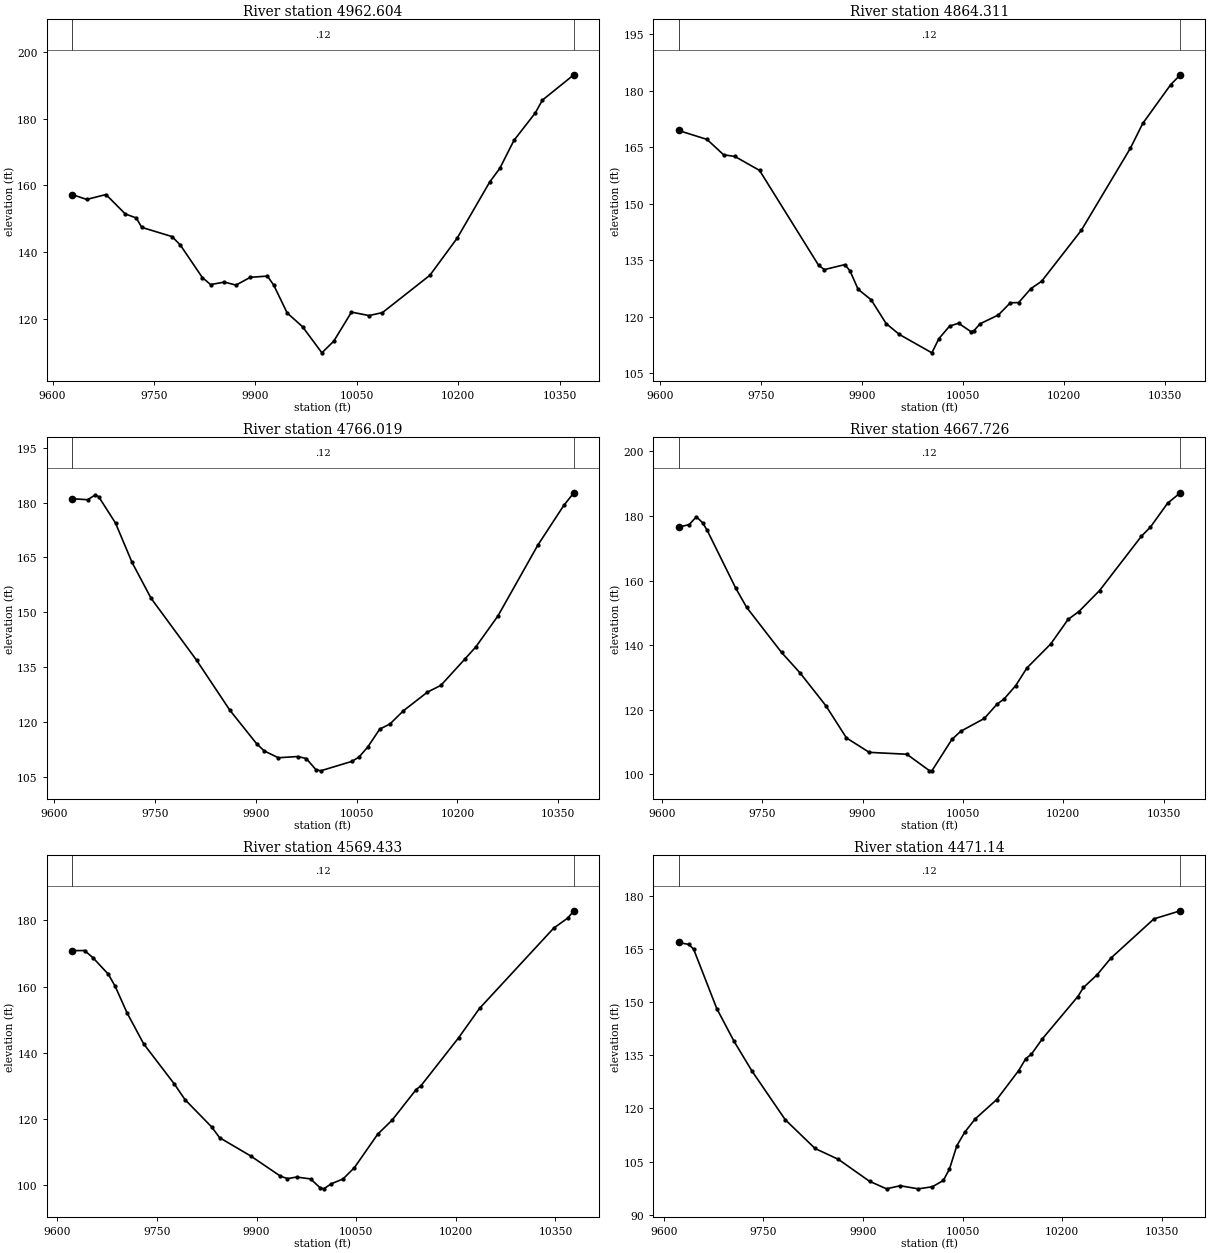
Type RM Length L Ch R = 1 ,4962.604,98.292700,98.292700,98.292700
XS GIS Cut Line= 6
1233319.71637833 631981.432377411233093.40246505631811.056269107
1233059.95134427631774.0056244831233027.86234104631705.744460218
 1232987.0064348631654.3906559591232781.77112498631482.810602915
#Sta/Elev= 30
9628.843  157.26 9650.51155.7969 9679.01157.26339707.511 151.4649723.764150.2478
 9731.94147.43849776.726144.67969788.941 142.1659821.513132.42729833.727130.3222
9854.337131.05799871.278130.15489892.453132.48189917.773132.8557 9927.07130.1884
9947.097121.81279969.778117.70639998.417109.882910015.97113.3782 10042.2122.0705
10068.16121.036110088.04121.929610158.19133.097310198.49 144.192 10246.7161.0122
10261.57165.0888 10282.6173.490210313.88181.618910324.66185.526110371.17193.1064
#Mann= 3 , 0 , 0
9628.843    0.12       09628.843    0.12       010371.17    0.12       0
#XS Ineff= 2 , 0
       0                               0
Bank Sta=9628.843,10371.17
Exp/Cntr=0.3,0.1

Type RM Length L Ch R = 1 ,4864.311,98.292800,98.292800,98.292800
XS GIS Cut Line= 6
1233404.63595643631923.1698835211233205.77054709631767.819995888
1233159.74092187631725.1398523261233093.90990075631651.066677311
1233047.63100717631606.7136703851232838.15510114631440.080630833
#Sta/Elev= 30
 9626.98169.43539669.214167.07629694.045162.98259710.598162.55799747.415158.8457
9835.357133.62739843.809132.51919874.269133.84539881.994132.16719893.941127.2911
9913.242124.53029935.684118.19859955.336115.306210003.66110.431810014.02114.1903
10029.98117.5214 10043.3118.288610061.65116.0638 10066.2116.317710075.29118.1321
10102.55  120.4910120.26123.711110132.64123.772110150.97127.492610166.83129.4277
10225.85 142.95710298.74164.722510317.17171.308710358.68181.584610373.03184.2199
#Mann= 3 , 0 , 0
 9626.98    0.12       0 9626.98    0.12       010373.03    0.12       0
#XS Ineff= 2 , 0
       0                10046.85       0
Bank Sta=9626.98,10373.03
Exp/Cntr=0.3,0.1

Type RM Length L Ch R = 1 ,4766.019,98.292800,98.292800,98.292800
XS GIS Cut Line= 6
1233491.16213715631805.3202992021233281.95128258631657.258065684
1233219.66558537631623.1831020391233135.61463674631588.009717384
 1233083.5059027631557.2853776971232866.93970426631401.239276355
#Sta/Elev= 30
9626.996181.07629650.133180.77919661.605182.12459666.724181.5633 9691.61174.3897
  9716.1163.65819744.468153.80479812.092 136.865 9861.44123.21529901.431113.9935
 9912.65112.04289933.509110.17399962.469110.50549975.133109.96049989.341106.9488
9996.446 106.58810042.73109.164110053.42110.334610066.34113.044910084.43118.0086
10099.66119.416110119.33122.986510155.28128.124410175.26129.977110211.22137.2288
10227.39140.546210260.03148.951710319.43168.358110358.05179.2321   10373182.6866
#Mann= 3 , 0 , 0
9626.996    0.12       09626.996    0.12       0   10373    0.12       0
#XS Ineff= 2 , 0
       0                               0
Bank Sta=9626.996,10373
Exp/Cntr=0.3,0.1

Type RM Length L Ch R = 1 ,4667.726,98.292800,98.292800,98.292800
XS GIS Cut Line= 6
1233534.20090076631721.6803982571233453.80233337631659.720847776
1233382.59455875631610.7660022031233059.29516054631428.490417522
1232973.95154823631372.5454723931232901.91312645631320.134671135
#Sta/Elev= 30
9624.878176.53139640.789177.33329651.539 179.772  9660.9177.89059667.663175.5703
9710.605157.55589726.816 151.655  9778.9137.7253 9806.77131.33259845.292121.1838
9875.926111.23779910.032106.7709 9966.23106.18259999.945101.105710003.67101.0414
10033.51110.758910046.86113.3069   10082 117.25910100.65  121.6110111.84 123.352
10128.96127.434810145.88132.950310181.35140.345610207.32147.960810223.47150.3939
10254.39156.908110316.96173.7348 10330.4176.5519   10356 183.93910375.13187.1906
#Mann= 3 , 0 , 0
9624.878    0.12       09624.878    0.12       010375.13    0.12       0
#XS Ineff= 2 , 0
       0                               0
Bank Sta=9624.878,10375.13
Exp/Cntr=0.3,0.1

Type RM Length L Ch R = 1 ,4569.433,98.292700,98.292700,98.292700
XS GIS Cut Line= 6
1233579.10697667 631635.446809541233461.66648556631539.906114654
1233371.59779823631477.3844240061233133.80919768631378.591405928
1233034.53224463631318.4832171271232937.32253376631247.829495617
#Sta/Elev= 30
9622.304170.88939641.098170.91929653.892168.72839676.884163.77089687.109160.1599
9705.091152.09629730.178142.72539776.107130.6747 9792.39 125.8969832.415117.6766
9844.409114.42759891.419108.88349935.612102.86399946.422102.07339960.406102.5483
9981.382101.98269995.36599.36717   1000198.9902410012.82100.5448 10030.1101.9519
10047.38105.413510082.43115.499410104.07119.731410140.14128.934110147.63130.1415
 10204.4144.649910235.61153.448210347.13177.6474 10368.6180.749710377.65182.9219
#Mann= 3 , 0 , 0
9622.304    0.12       09622.304    0.12       010377.65    0.12       0
#XS Ineff= 2 , 0
       0                               0
Bank Sta=9622.304,10377.65
Exp/Cntr=0.3,0.1

Type RM Length L Ch R = 1 , 4471.14,98.292800,98.292800,98.292800
XS GIS Cut Line= 6
1233578.58760586631574.5439584681233334.15313808 631363.74200249
1233305.11306302631344.2151969841233250.91132431631319.148118575
1233193.75200947631281.5678138761232982.94459675631113.966678597
#Sta/Elev= 30
9622.332166.77989637.896166.20719645.054164.88089679.839148.15599705.927138.8937
9732.886130.5298 9782.88116.82529827.875108.69549862.871105.64489909.796 99.4564
9935.40197.328779955.884 98.19359983.22697.3224410004.5697.9110610020.8699.68113
10030.05 102.84310041.28109.487310053.46113.360310068.77117.010210101.23122.4757
10134.41 130.67910145.11134.045910153.35135.232810169.84139.571710223.42151.5322
10231.92154.077210252.55157.693610273.17162.359710338.02173.424410377.68175.7025
#Mann= 3 , 0 , 0
9622.332    0.12       09622.332    0.12       010377.68    0.12       0
#XS Ineff= 2 , 0
       0                               0
Bank Sta=9622.332,10377.68
Exp/Cntr=0.3,0.1

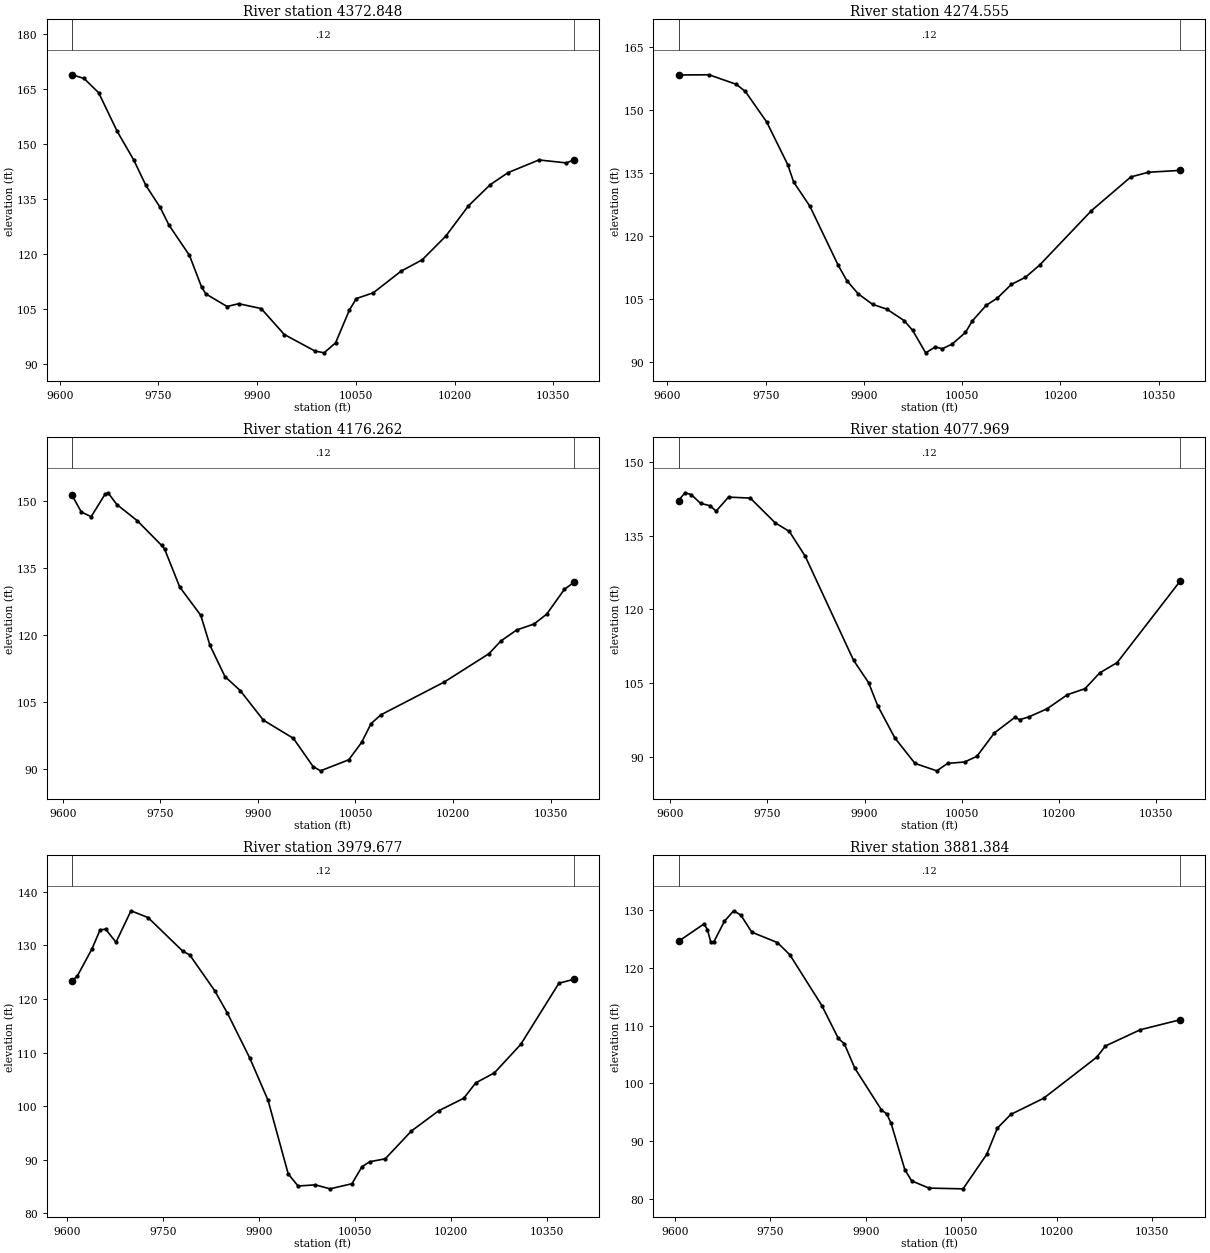
Type RM Length L Ch R = 1 ,4372.848,98.292800,98.292800,98.292800
XS GIS Cut Line= 6
1233614.19732901631574.4973609061233415.62052465631383.189428963
1233387.62999669631340.8927880271233348.56747352631240.056102763
1233315.09804375 631183.657078971233136.49644202630992.486990652
#Sta/Elev= 30
 9618.74168.86929636.895167.87379659.146163.97349687.204153.47119712.547145.5924
9730.908138.68599752.598132.69069765.949127.86889797.135119.59399815.593110.9229
9822.112109.08449854.265105.64459871.816106.40889906.032105.0963 9941.2698.00478
9987.65693.5175210001.6593.0073410019.1795.73328 10040.2104.699310050.71107.8163
10076.48109.395210118.79115.298410150.76118.379310186.63124.8523 10221.1133.1227
10254.17138.881110281.29 142.17810328.18145.633310369.67144.828510381.24145.6428
#Mann= 3 , 0 , 0
 9618.74    0.12       0 9618.74    0.12       010381.24    0.12       0
#XS Ineff= 2 , 0
       0                               0
Bank Sta=9618.74,10381.24
Exp/Cntr=0.3,0.1

Type RM Length L Ch R = 1 ,4274.555,98.292700,98.292700,98.292700
XS GIS Cut Line= 6
1233718.70911743631528.4387071391233549.14549081631355.545530396
 1233448.8985642631241.8178133621233326.28383938631096.113450829
1233274.28587126631040.3594007271233199.71711058630965.454777417
#Sta/Elev= 30
9616.922 158.4189663.487158.46799705.146156.1886 9718.94154.48429751.497147.2061
 9783.63137.03089792.702132.86459817.535127.06969860.684113.0009 9873.81109.3512
9891.311106.16469913.187103.67279935.064 102.5129961.31699.800389974.44297.44839
9994.237 92.093910009.1893.5248310019.35 93.047110034.6394.1818810055.0196.95546
 10065.299.6554510086.59103.426210103.74105.171710125.18108.436710146.62110.1324
10168.06113.007310247.28126.024610307.48134.079710334.28135.200910383.07135.6476
#Mann= 3 , 0 , 0
9616.922    0.12       09616.922    0.12       010383.07    0.12       0
#XS Ineff= 2 , 0
       0                               0
Bank Sta=9616.922,10383.07
Exp/Cntr=0.3,0.1

Type RM Length L Ch R = 1 ,4176.262,98.292800,98.292800,98.292800
XS GIS Cut Line= 6
1233788.49252117631440.0682037891233707.71351521631356.180647327
1233615.62530362631264.1234841251233558.39968662631209.890366721
1233453.00609494631117.3086446131233236.66786402630901.080186878
#Sta/Elev= 30
9614.159151.25169628.392147.48929643.508146.44789664.829151.47179669.383151.8015
9683.047149.17479714.456145.54179751.879140.01199756.518139.17569779.713130.6947
9812.086124.35529826.103117.66859849.298110.63059872.735107.50739908.355100.8775
9954.59496.789859984.78390.491399996.23889.52226 10039.691.9886210059.3795.87128
 10073.9100.090310089.01102.059110186.42109.404110255.16115.749110273.72118.6197
10297.75121.057110324.77122.423510344.13124.625410371.18130.162210385.84131.7334
#Mann= 3 , 0 , 0
9614.159    0.12       09614.159    0.12       010385.84    0.12       0
#XS Ineff= 2 , 0
       0                               0
Bank Sta=9614.159,10385.84
Exp/Cntr=0.3,0.1

Type RM Length L Ch R = 1 ,4077.969,98.292800,98.292800,98.292800
XS GIS Cut Line= 6
1233856.92256292631390.0450777571233777.12164267 631304.79827647
1233631.72436008 631160.512258621233565.84664059631080.988549832
1233542.36194889631055.6360396131233313.36548195630839.804834316
#Sta/Elev= 30
9612.926142.13139622.827143.70189632.428143.34989646.831141.55749661.811141.0574
9670.834139.96289690.037142.82039723.642142.62219761.808137.61659783.955135.8301
9808.385130.78579882.908109.64599906.197105.0695 9920.17100.39429946.494 93.8714
9977.66488.6628110011.3387.14843 10028.188.6631510054.2888.9479810073.2290.10066
10100.2794.8629710131.8398.0272210139.1297.5491910153.4798.1229510181.4399.76247
10212.98102.646610240.03103.852510262.58107.055410289.63109.166810387.07125.7857
#Mann= 3 , 0 , 0
9612.926    0.12       09612.926    0.12       010387.07    0.12       0
#XS Ineff= 2 , 0
       0                               0
Bank Sta=9612.926,10387.07
Exp/Cntr=0.3,0.1

Type RM Length L Ch R = 1 ,3979.677,98.292800,98.292800,98.292800
XS GIS Cut Line= 6
1233940.63611046631292.4915644991233858.94850377631199.936159009
1233774.52097797631119.8412732821233710.58206967631070.987699257
1233546.09169527 630965.587152811233346.70887616630787.239290336
#Sta/Elev= 30
9608.248123.43829616.226124.23119639.057129.28059651.996132.88539660.621133.0329
9676.826130.58549700.227136.4599 9726.96135.19019781.098128.91949791.931128.2281
9830.983121.53829850.841117.33869885.888108.92699914.266101.07839945.75587.33859
9961.12485.080189988.02185.2978210011.0684.5539510045.3185.5118410060.8888.68067
10072.9889.6133210097.1990.1568910138.1895.3571910180.59 99.117610219.76 101.459
10238.58104.3377 10267.7106.202310308.78111.512910368.45122.940610391.75 123.671
#Mann= 3 , 0 , 0
9608.248    0.12       09608.248    0.12       010391.75    0.12       0
#XS Ineff= 2 , 0
       0                               0
Bank Sta=9608.248,10391.75
Exp/Cntr=0.3,0.1

Type RM Length L Ch R = 1 ,3881.384,98.292700,98.292700,98.292700
XS GIS Cut Line= 6
1233976.72051249631220.3145823991233900.42212645631127.261616264
1233828.23946863631053.3513955441233779.45776339631011.674965656
 1233563.8056386630844.1561608941233398.26627735630688.922199523
#Sta/Elev= 30
9606.032124.58789646.091127.60469651.378126.62279656.665124.43089661.023124.3917
9678.021128.05349692.608129.87749703.887129.12339721.131126.16669761.157124.3763
 9780.72122.27169831.109113.45299856.999107.76129866.364106.8472 9882.89102.6012
9924.73695.373789933.016 94.69359939.88493.038059961.40285.02103 9972.16 83.0944
 9999.2481.8432210052.8181.7157610089.9787.6902210106.7292.2320610127.8294.60673
10179.27 97.400410262.99104.537110276.24106.451810331.14 109.27210393.98111.0081
#Mann= 3 , 0 , 0
9606.032    0.12       09606.032    0.12       010393.98    0.12       0
#XS Ineff= 2 , 0
       0                               0
Bank Sta=9606.032,10393.98
Exp/Cntr=0.3,0.1