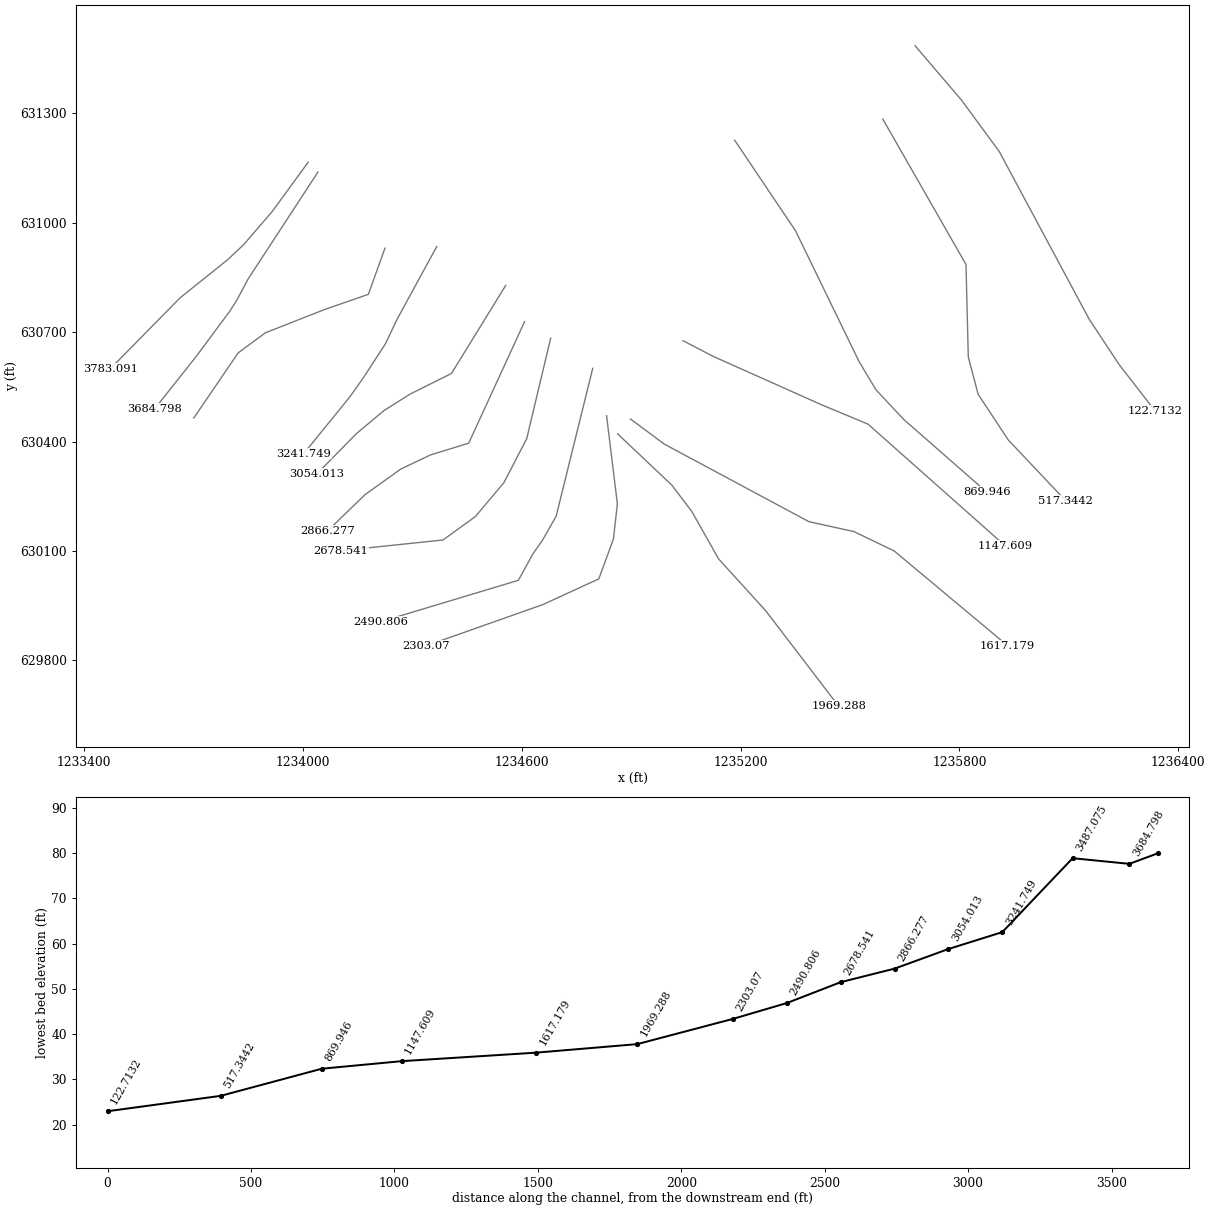
HEC-RAS study 689_ras.prj: 689

--- 689_ras.g01 (geometry) --- (continued)

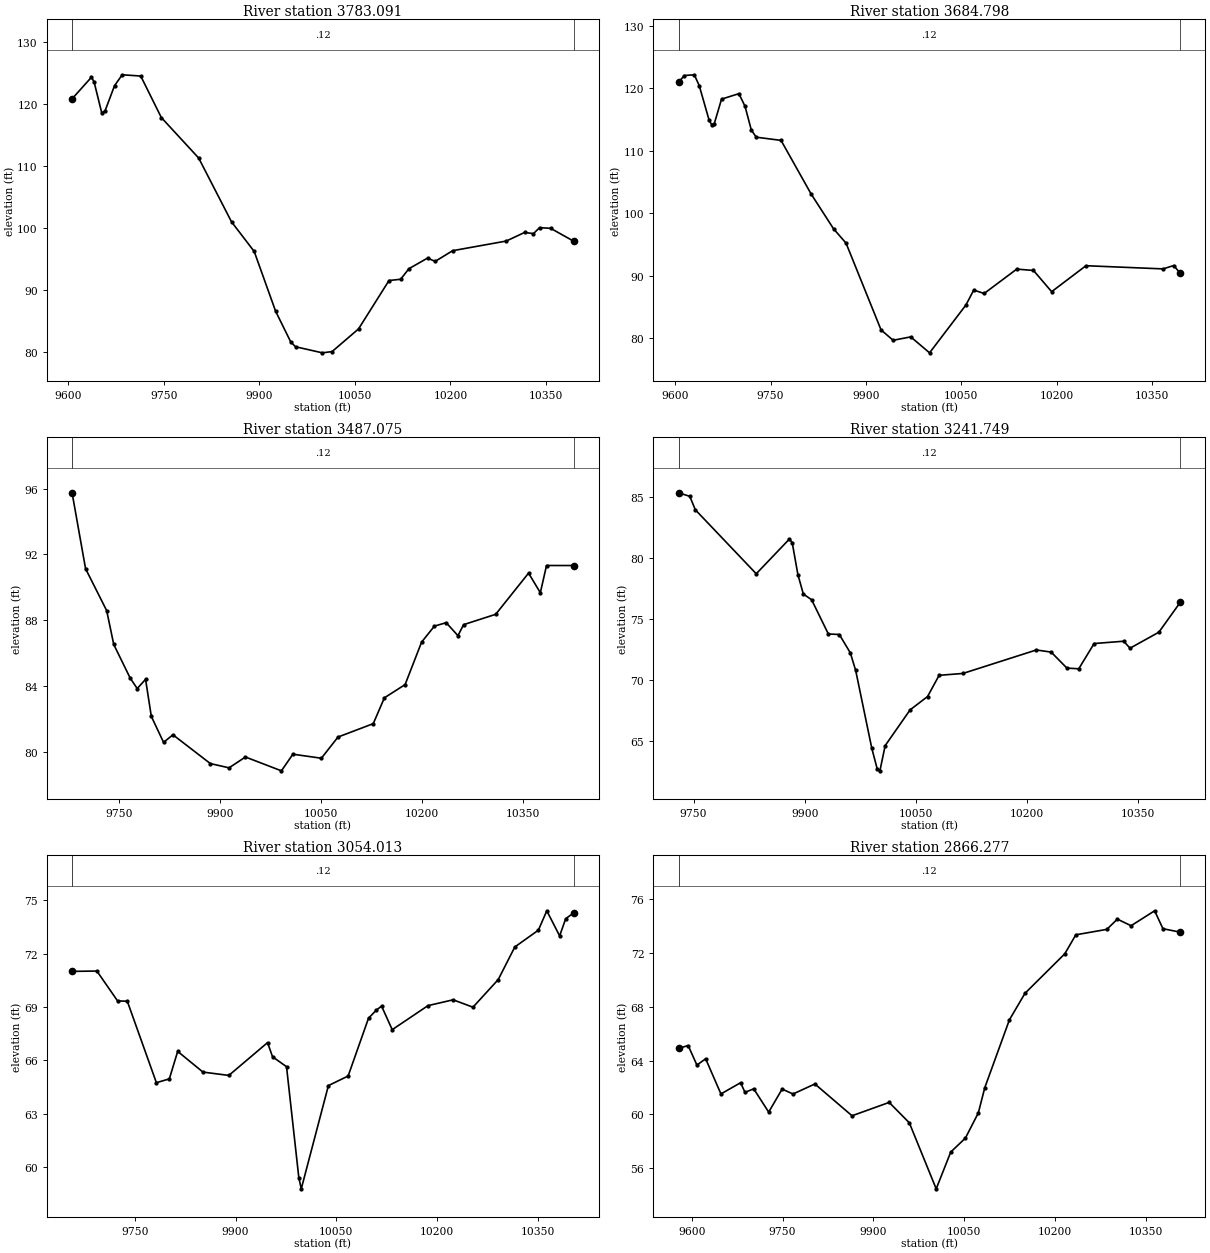
Type RM Length L Ch R = 1 ,3783.091,98.292800,98.292800,98.292800
XS GIS Cut Line= 6
1234014.52202637631165.9988385371233915.70487901631030.569280348
1233837.20625415630939.596532176 1233793.0820894630898.193095639
1233663.32152153630794.1504098381233471.78164968630599.553454681
#Sta/Elev= 30
9606.059120.84699636.558124.33969640.701 123.5539652.634118.5865 9657.74118.8767
 9672.73122.96619684.787124.72519713.868124.52319746.187117.83569804.853111.3064
9856.441101.0207 9892.0696.247669925.65886.616769949.45281.659919956.915 80.8955
    999979.9107310014.3380.1135110055.8683.76708 10103.791.5646610122.0491.77084
10134.8793.46387 10164.3 95.184410176.1494.6451910203.6596.3747510287.7497.92649
10316.6599.3138710330.5599.1276410340.07100.083310357.4299.9824910393.9697.88572
#Mann= 3 , 0 , 0
9606.059    0.12       09606.059    0.12       010393.96    0.12       0
#XS Ineff= 2 , 0
       0                               0
Bank Sta=9606.059,10393.96
Exp/Cntr=0.3,0.1

Type RM Length L Ch R = 1 ,3684.798,197.723100,197.723100,197.723100
XS GIS Cut Line= 6
1234041.24126184631138.9597113921233850.34120696630846.632878656
1233818.61482372630787.2514319661233799.03113092 630756.81491274
1233707.88205537630633.9975415141233593.73971061630489.974203187
#Sta/Elev= 30
9605.282120.97689614.434122.06759630.034122.18659637.833120.45389653.433114.8877
9657.333114.19879661.371114.29869672.933118.28199700.232119.16149709.919117.1252
9719.732113.34339727.532112.18039766.531111.66839813.697103.10289849.12297.49578
9868.80295.195229923.907 81.27849942.88779.618959970.57980.16379 10000.277.60572
10057.4785.28467 10069.787.6694810086.0587.1197410137.3591.0292210163.6790.81578
10192.2787.4092710246.2391.5740510367.4691.0652910384.3891.60295 10394.790.34156
#Mann= 3 , 0 , 0
9605.282    0.12       09605.282    0.12       0 10394.7    0.12       0
#XS Ineff= 2 , 0
       0                               0
Bank Sta=9605.282,10394.7
Exp/Cntr=0.3,0.1

Type RM Length L Ch R = 1 ,3487.075,245.326000,245.326000,245.326000
XS GIS Cut Line= 6
1234224.94555736 630930.305450411234179.50283033630803.714996427
1234057.78123996630761.5181784331233897.10874066630698.222951472
1233822.45283195630643.0424971881233700.73124155630464.517498001
#Sta/Elev= 30
9680.42795.745289700.467 91.13319731.83988.582459742.29786.529029766.69784.48748
9777.15583.851219789.53584.41138 9798.0782.161449816.26480.582029830.15481.04329
9885.71279.293319913.491 79.03479937.79879.692749991.21878.8520710008.2379.86266
10050.5479.6175710075.2380.9058610127.5481.71852 10144.183.2888910174.8384.09216
10199.3186.6724110218.3487.6442410235.81 87.853610253.2987.0641510261.6687.73251
10309.3188.3626710358.1290.8647910375.5989.6725310384.7691.3268910425.3591.32563
#Mann= 3 , 0 , 0
9680.427    0.12       09680.427    0.12       010425.35    0.12       0
#XS Ineff= 2 , 0
       09936.785                       0
Bank Sta=9680.427,10425.35
Exp/Cntr=0.3,0.1

Type RM Length L Ch R = 1 ,3241.749,187.735900,187.735900,187.735900
XS GIS Cut Line= 6
1234366.90924895630934.6084225941234258.11674191630735.171813266
1234226.68846802630668.7926677341234167.35167162630577.250090517
1234129.34976957630523.4095816531234002.32793273630367.039419439
#Sta/Elev= 30
 9729.79 85.30679744.96485.015549752.43983.914049834.65878.670269879.50481.52155
9883.24281.208999890.83478.609359898.19177.011749909.40276.538679931.94173.73786
9946.77573.694359961.58772.193199968.84770.745359990.62864.359139997.88862.67973
10001.5262.5229610008.65  64.59110042.35 67.5238 10065.868.6083610081.4470.34997
 10113.570.5021810212.65  72.427 10232.672.2525810253.8970.9417210269.8770.88439
10290.5972.9536110330.5373.1436910339.0572.5704910378.0373.8848910406.9376.33935
#Mann= 3 , 0 , 0
 9729.79    0.12       0 9729.79    0.12       010406.93    0.12       0
#XS Ineff= 2 , 0
       0                10104.85       0
Bank Sta=9729.79,10406.93
Exp/Cntr=0.3,0.1

Type RM Length L Ch R = 1 ,3054.013,187.735800,187.735800,187.735800
XS GIS Cut Line= 6
1234556.02828309630828.0593145041234407.39047062630586.801208095
1234294.25155322630530.4297969011234222.13972198630484.973811226
1234146.08654113630421.1804180761234038.95526434630312.091895098
#Sta/Elev= 30
9656.48271.000169693.41471.019399724.24269.343919738.73369.325049782.04564.75291
9801.31364.96556 9813.7966.509339851.40865.348339889.94365.161169947.62467.00231
9955.03766.207219975.87365.651299994.167 59.42869997.82558.7952510038.2264.58914
10067.6365.1283110097.9668.3702710109.5168.8214110117.43 69.051910133.26 67.7279
10186.5169.0772410223.96 69.404810253.5368.9897810291.1770.5407910315.8672.37023
10350.9373.31154 10363.5 74.4014 10382.672.9905110391.6573.9585110403.7974.28805
#Mann= 3 , 0 , 0
9656.482    0.12       09656.482    0.12       010403.79    0.12       0
#XS Ineff= 2 , 0
       09925.906        10124.07       0
Bank Sta=9656.482,10403.79
Exp/Cntr=0.3,0.1

Type RM Length L Ch R = 1 ,2866.277,187.735900,187.735900,187.735900
XS GIS Cut Line= 6
1234607.96282834630729.0590876941234454.58856578630395.651745835
1234350.23246655630363.6079486011234268.26141753630324.597787294
1234170.55707462630254.6596205371234068.43363939630155.919117115
#Sta/Elev= 30
9578.07164.911319593.99365.122059608.43863.669299622.883 64.13739648.163 61.5227
9680.66562.357989687.88761.637989702.33361.903919727.07160.16956 9749.2861.88187
9767.33761.51906 9803.4562.263869864.84259.898249926.23560.891849959.53259.37547
10003.9754.46263   10028  57.19810052.2558.23737 10073.660.1101910084.3161.99165
10125.0467.0401510150.7569.0092410216.55 71.948810234.7773.3597710286.0873.76456
10303.3974.5275510326.0774.0338610365.0375.1471910378.7573.81357 10407.573.55393
#Mann= 3 , 0 , 0
9578.071    0.12       09578.071    0.12       0 10407.5    0.12       0
#XS Ineff= 2 , 0
       09835.022                       0
Bank Sta=9578.071,10407.5
Exp/Cntr=0.3,0.1

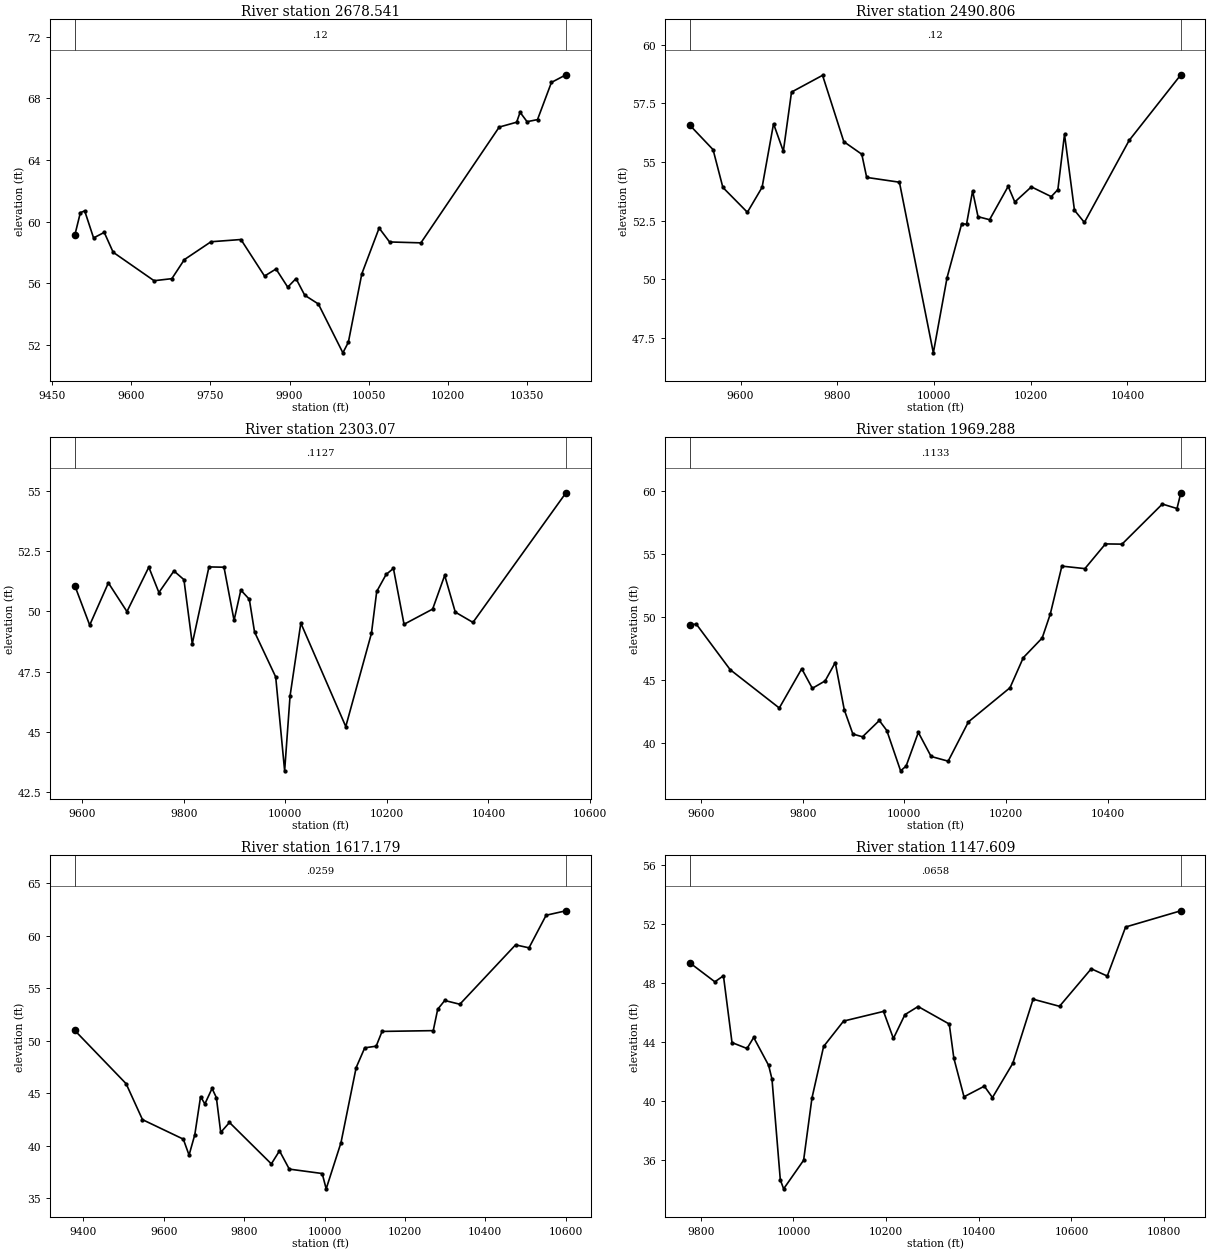
Type RM Length L Ch R = 1 ,2678.541,187.735900,187.735900,187.735900
XS GIS Cut Line= 6
1234679.37282798 630683.616360621234613.66755021630408.062041253
1234551.03665569630287.2798068971234472.71722764630194.270573005
1234383.99510208630130.1888631581234104.84692156630100.975681484
#Sta/Elev= 30
9492.80559.105959503.35460.573979511.55160.691569528.415 58.93489548.65259.29436
9565.51658.006119643.09156.158299676.81956.292239700.42857.526079751.02158.68723
9807.75258.832199852.47856.460029874.275 56.92069896.449 55.7409 9912.1456.29715
9928.69155.215689954.52154.64877   1000151.4783910011.3952.1680210036.8556.60267
10069.6859.5750910089.4758.6739110148.8958.6149110297.3366.1280210330.3266.44386
10336.9267.0862710350.1166.4778410369.9166.61274 10396.369.0263510423.9169.52197
#Mann= 3 , 0 , 0
9492.805    0.12       09492.805    0.12       010423.91    0.12       0
#XS Ineff= 2 , 0
       09802.493                       0
Bank Sta=9492.805,10423.91
Exp/Cntr=0.3,0.1

Type RM Length L Ch R = 1 ,2490.806,187.735800,187.735800,187.735800
XS GIS Cut Line= 6
1234794.60260019630600.8456791791234694.43293107630195.585845074
1234656.72901141630129.4176586391234630.93112581630092.654959853
1234590.88500064630019.7253883491234213.58487558629906.221136913
#Sta/Elev= 30
9494.69456.577549543.12155.527219563.39853.916419614.092 52.85769644.50853.92182
9668.16556.630449688.44255.45884 9705.3457.980969769.55258.695879813.48655.86833
9850.66255.33196  9860.854.34374 9928.4954.139739998.63546.8657910027.0750.07704
10057.3652.3747410067.2452.3459710079.82 53.764710091.0552.6691910114.9552.54133
 10153.453.9637210167.1153.2960710201.3753.9410410242.48 53.525310256.1853.82474
10269.8956.1814410290.4552.94499   1031152.4244210403.5255.9195310510.4958.71894
#Mann= 3 , 0 , 0
9494.694    0.12       09494.694    0.12       010510.49    0.12       0
#XS Ineff= 2 , 0
       09864.955        10089.75       0
Bank Sta=9494.694,10510.49
Exp/Cntr=0.3,0.1

Type RM Length L Ch R = 1 , 2303.07,333.782000,333.782000,333.782000
XS GIS Cut Line= 6
1234832.58218616630471.0723761321234862.20979586630229.246247098
1234851.35000885630132.5314292761234811.29481164630023.571165189
1234658.27441901629953.2868185041234336.92942053629839.680000871
#Sta/Elev= 30
9585.59251.07603 9614.93 49.43139651.71151.188479688.29749.994399731.32651.84272
9751.18650.787529780.76351.68408 9800.4751.322249816.87448.657469849.73951.85229
9879.35151.839999899.16449.630119912.50850.888619929.23350.505659939.46649.14794
9981.12447.278129998.74443.37096 10009.446.4847810030.6349.51545 10119.1 45.2124
10169.6549.0906210180.0250.8303110198.5351.5391510212.9351.7898810233.8149.46615
10290.1250.0982910313.8551.4999510334.7349.9721210369.5249.5442910552.6754.93591
#Mann= 3 , 0 , 0
9585.592  0.1127       09585.592  0.1127       010552.67  0.1127       0
#XS Ineff= 2 , 0
       09946.982        10181.92       0
Bank Sta=9585.592,10552.67
Exp/Cntr=0.3,0.1

Type RM Length L Ch R = 1 ,1969.288,352.109000,352.109000,352.109000
XS GIS Cut Line= 6
1234862.89779615630421.1686744191235011.74406628630280.415710937
1235066.46638398630208.1505423841235139.64136477630078.476197315
1235268.89950975629936.2323266571235468.54746743  629675.0885856
#Sta/Elev= 30
9577.81149.350719590.767 49.44019657.56345.815929754.052 42.77739798.19645.89385
9819.02544.339159844.14844.926049864.11646.383739881.80342.640489898.774 40.7095
9917.74440.493969950.72441.786689965.43340.992579992.57837.7921310003.4338.17033
10027.4540.8413510052.5638.9324710086.0938.5588610125.9641.6795110207.7144.38634
10233.8246.7712410270.9848.33241 10286.950.2328610309.6754.0348610354.9553.83643
10395.3655.7974110427.9655.7790910507.23 58.960810536.0458.6054110543.6259.85428
#Mann= 3 , 0 , 0
9577.811  0.1133       09577.811  0.1133       010543.62  0.1133       0
#XS Ineff= 2 , 0
       0                               0
Bank Sta=9577.811,10543.62
Exp/Cntr=0.3,0.1

Type RM Length L Ch R = 1 ,1617.179,469.570000,469.570000,469.570000
XS GIS Cut Line= 6
 1234898.1575135630461.8720019161234990.94101739 630393.06759806
1235387.26393741630180.5094888661235510.42087066630153.383120984
1235621.01922074630100.2934169021235932.19462308629840.425003096
#Sta/Elev= 30
9378.49750.974519506.19345.910619546.95642.491749648.555 40.63769662.86539.12034
9677.175  41.0649691.48544.677589702.21843.987839720.10545.461229730.838 44.5825
9741.62741.278319763.43742.222279867.60938.283489887.90339.524169912.25637.78801
9994.14537.3678310004.0635.9112610040.9140.3015610078.6647.4414410100.0249.32245
10128.4949.4786910143.1350.88215 10270.550.95805 10281.652.9910910299.1253.82352
 10336.753.4664310475.3359.11339 10508.8 58.832910551.3961.9314310600.8462.35588
#Mann= 3 , 0 , 0
9378.497  0.0259       09378.497  0.0259       010600.84  0.0259       0
#XS Ineff= 2 , 0
       0                               0
Bank Sta=9378.497,10600.84
Exp/Cntr=0.3,0.1

Type RM Length L Ch R = 1 ,1147.609,277.662800,277.662800,277.662800
XS GIS Cut Line= 5
1235042.00522029630676.7538871471235125.27797252630633.435233206
1235422.22367382630500.8701879381235549.48611727630447.844169855
1235925.97084579630113.780255839
#Sta/Elev= 30
9775.86449.393549830.31548.093999848.80648.505379867.29743.965989899.70343.56368
9914.07544.313689946.41142.413169953.59741.479939971.56134.637679978.747  34.028
10021.8635.9709510039.8340.19191   1006543.7008910108.0945.4265110194.3246.08324
10215.65 44.244610240.5345.8638510268.9746.4168510336.2245.2253110346.1442.90399
10368.0740.2815610411.9341.0033810429.4840.2301110473.3442.55441 10517.246.91414
10574.2246.43058 10642.748.98081 10677.348.4860210716.8551.8185810836.1252.92139
#Mann= 3 , 0 , 0
9775.864  0.0658       09775.864  0.0658       010836.12  0.0658       0
#XS Ineff= 2 , 0
       0                10101.02       0
Bank Sta=9775.864,10836.12
Exp/Cntr=0.3,0.1

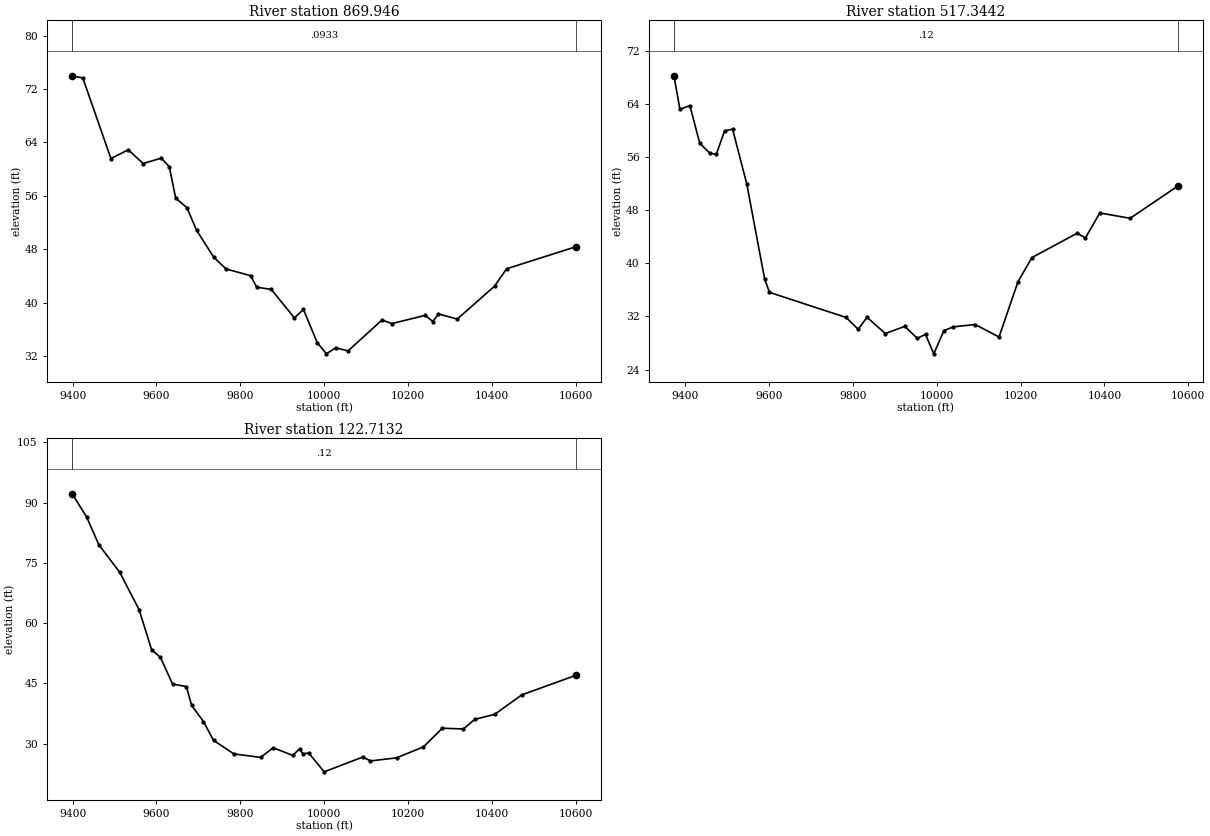
Type RM Length L Ch R = 1 , 869.946,352.601800,352.601800,352.601800
XS GIS Cut Line= 6
1235183.68891418631226.4249676261235350.67606508630977.969414106
1235524.51791228630620.1562241791235570.89955992630542.398566746
1235647.49269069630460.5333633221235874.33830365630261.953262791
#Sta/Elev= 30
9399.05873.979499424.42873.653539491.51161.594459532.80262.896819568.378 60.8517
9611.61361.649149630.75760.376929646.07255.671659672.87454.238169695.847 50.8603
9736.66846.831189766.28945.064999824.88944.060689839.27742.341069874.16842.00932
9929.199 37.74189950.78139.013349983.57934.0615510005.6332.3675610028.0233.27998
10056.9932.79574 10138.337.4338510161.7236.8956410241.2738.1270810259.4937.20252
10272.8838.3441610317.6137.5697310406.8242.4979810435.3345.09352 10600.948.39814
#Mann= 3 , 0 , 0
9399.058  0.0933       09399.058  0.0933       0 10600.9  0.0933       0
#XS Ineff= 2 , 0
       0                10128.47       0
Bank Sta=9399.058,10600.9
Exp/Cntr=0.3,0.1

Type RM Length L Ch R = 1 ,517.3442,394.631000,394.631000,394.631000
XS GIS Cut Line= 6
1235589.85171214631284.2601522911235817.97987776630885.743224242
1235824.33656206630631.9741718261235851.50244224630529.306726143
1235934.06709973630404.3663348571236091.38069025 630237.93780766
#Sta/Elev= 30
 9373.2668.231139387.58263.162029411.22463.754379434.86758.07359 9458.5156.60161
9474.27156.397279493.97359.926639513.16660.202059547.09451.916819589.71437.60934
9601.19635.628449784.07631.845029812.78830.06805 9833.8731.87607 9877.6129.42654
9924.05530.508599953.62828.709569973.37329.298839993.13826.3720710017.1829.86837
10040.1130.43559 10091.830.7878510148.7528.9037810194.0437.2342510227.2140.86497
10335.2644.5313310354.8743.8218210389.1247.58092 10461.646.7768710575.0151.62031
#Mann= 3 , 0 , 0
 9373.26    0.12       0 9373.26    0.12       010575.01    0.12       0
#XS Ineff= 2 , 0
       0                               0
Bank Sta=9373.26,10575.01
Exp/Cntr=0.3,0.1

Type RM Length L Ch R = 1 ,122.7132,0.000000,0.000000,0.000000
XS GIS Cut Line= 6
1235678.40943385631485.3694172211235805.79631629631336.130692303
1235909.04340351631195.5771392441236155.52657901630736.025418958
1236237.58700714630611.5667322161236335.86263988630484.921335375
#Sta/Elev= 30
9399.03792.206339433.55586.430069462.70379.507259512.64872.631219558.81263.32664
9588.63853.337549609.52651.499189638.50644.842779671.62644.198299684.04639.50647
9712.32435.502989736.24630.809669784.98727.435139848.66926.576079878.77528.95861
9925.17227.073379941.653 28.70449949.04727.516039963.836 27.617910000.3422.97263
10092.4826.6628510110.7425.6868810172.9726.4559610237.0129.1829910282.2133.82739
10332.4133.65093 10359.636.0342910407.1437.2866910471.7542.1386510600.9547.00904
#Mann= 3 , 0 , 0
9399.037    0.12       09399.037    0.12       010600.95    0.12       0
#XS Ineff= 2 , 0
       0                               0
Bank Sta=9399.037,10600.95
Exp/Cntr=0.3,0.1